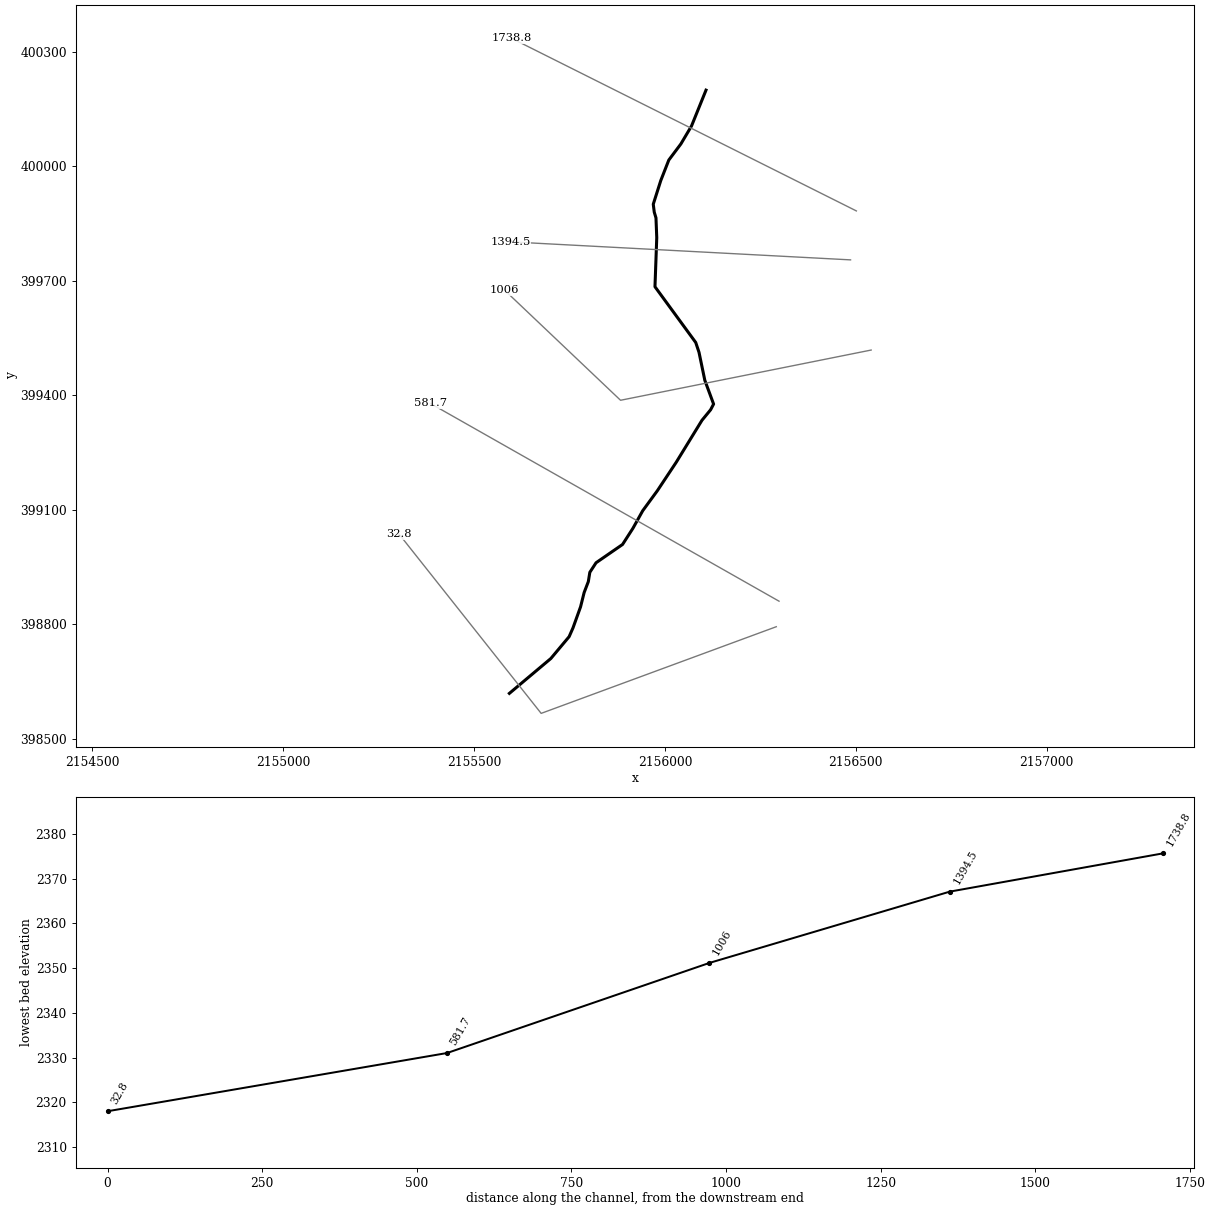
--- BoggsRun.prj (project) ---

Proj Title=BoggsRun
Current Plan=p01
Geom File=g01
Flow File=f01
Plan File=p01
DSS Export Rating Curves=0
DSS Export Rating Curve Sorted=0
DSS Export Volume Flow Curves=0
DXF OffsetX=0
DXF OffsetY=0
DXF ScaleX=0
DXF ScaleY=0

--- BoggsRun.p01 (plan) ---

Plan Title=Floodplain
Program Version=4.00
Geom File=g01
Flow File=f01
K Sum by GR=0
Std Step Tol=0.01
Critical Tol=0.01
Num of Std Step Trials=20
Max Error Tol=0.3
Flow Tol Ratio=0.001
Split Flow NTrial=30
Split Flow Tol=0.02
Split Flow Ratio=0.02
Log Output Level=0
Friction Slope Method=1
Unsteady Friction Slope Method=2
Unsteady Bridges Friction Slope Method=1
Global Log Level=0
CheckData=False
Run HTab=0
Run UNet=0
Run PostProcess=0
UNET Theta=0
UNET Theta Warmup=0
UNET ZTol=0
UNET ZSATol=0
UNET MxIter=0
UNET MaxInSteps=0
UNET DtIC=0
UNET DtMin=0
UNET MaxCRTS=0
UNET WFStab=0
UNET SFStab=0
UNET WFX=0
UNET SFX=0
UNET DSS MLevel=0
UNET DZMax Abort=0
UNET Convert EG Bridges=0
UNET Use Existing IB Tables=0
UNET Froude Limit=0
UNET Froude Power=0
Write IC File=0
Echo Input=False
Echo Output=False
Write Detailed=0

--- BoggsRun.f01 (steady flow) ---

Flow Title=NFF Regression Equation
Program Version=4.00
Number of Profiles=1
Profile Names=P100yr
River Rch & RM=BoggsRun,Main      ,1738.8
481.6342
River Rch & RM=BoggsRun,Main      ,1394.5
529.4808
River Rch & RM=BoggsRun,Main      ,32.8
558.0776
Boundary for River Rch & Prof#=BoggsRun,Main      ,1
Up Type=0
Dn Type=3
Dn Slope=0.034

--- BoggsRun.g01 (geometry) ---

Geom Title=USGS 10m DEM
Program Version=4.10

River Reach=BoggsRun        ,Main
Reach XY= 30
       2156107.5      400199.054     2156069.592      400105.183
      2156041.64      400057.981     2156010.074      400015.893
      2155989.03      399962.114     2155969.365      399900.129
      2155971.97      399879.283     2155976.442       399864.38
     2155978.508      399812.468     2155973.832      399683.865
     2156080.611      399537.726     2156089.158      399512.096
     2156104.383      399438.741     2156127.375      399376.389
     2156119.499      399361.397     2156096.971      399333.971
     2156029.559      399224.014     2155979.996      399149.245
     2155941.713      399096.874     2155916.156      399050.986
     2155888.876      399008.508      2155819.51      398960.594
      2155803.22      398935.534     2155799.244      398911.082
     2155788.333      398882.634      2155778.98      398845.222
     2155759.105      398789.884     2155748.972      398766.892
     2155701.039      398709.605     2155592.475      398618.307

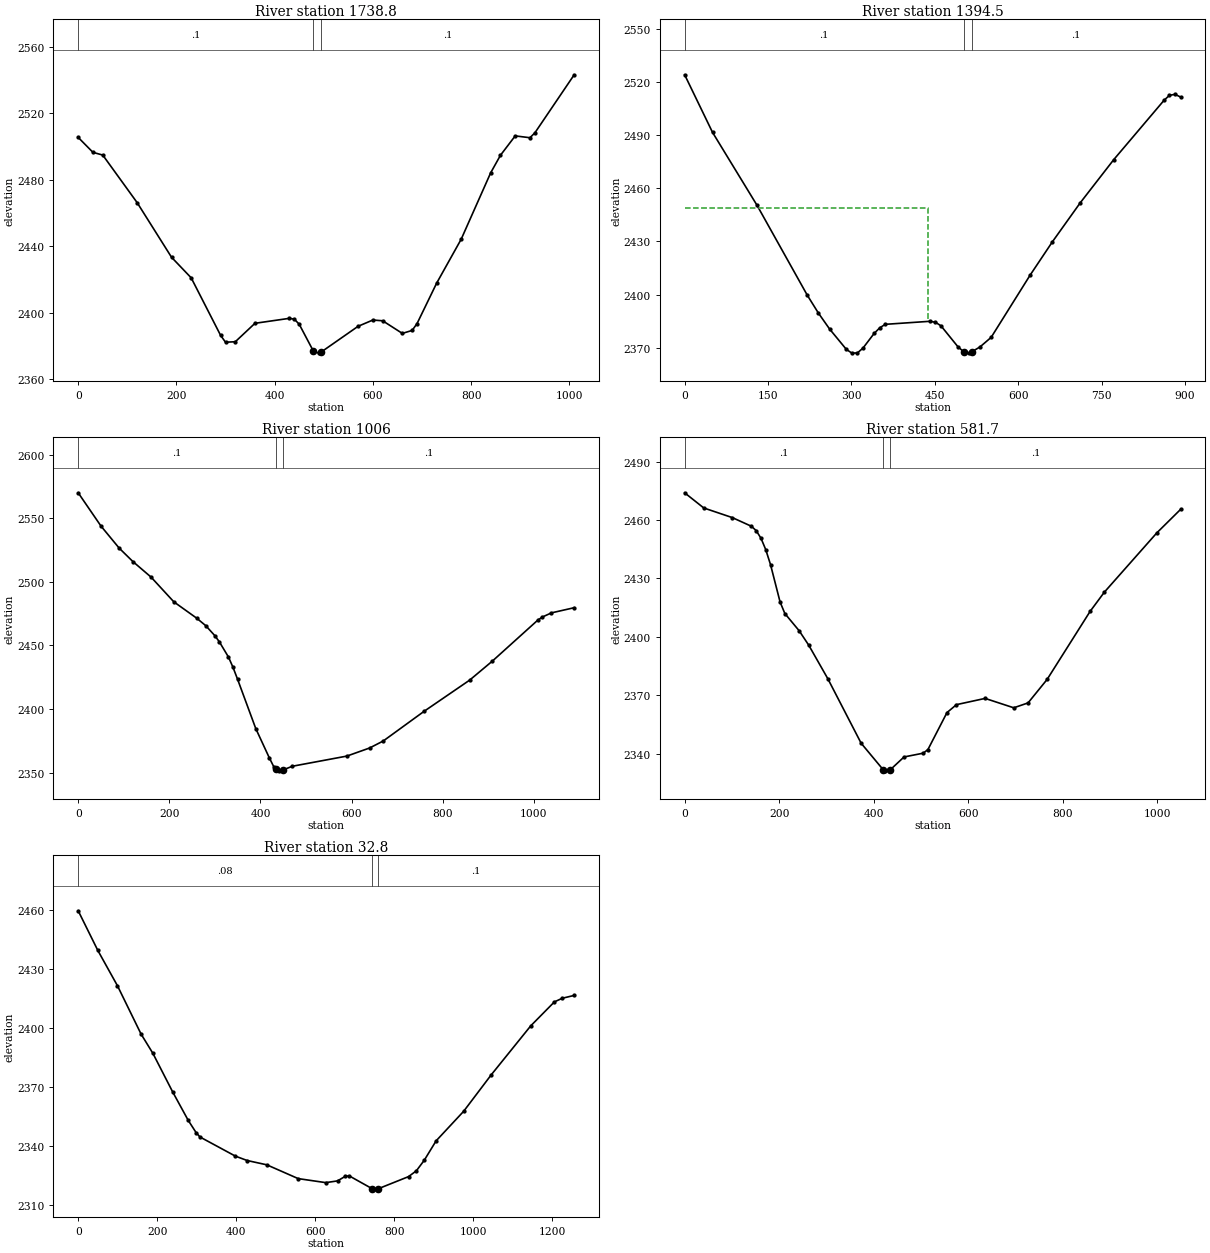
Type RM Length L Ch R = 1 ,1738.8  ,334.5,344.3,353.6
XS GIS Cut Line= 2
     2156501.318      399882.516     2155598.457       400334.79
#Sta/Elev= 30
       0 2505.42      30 2496.45      50  2494.8     120 2466.18     190 2433.32
     230 2420.94   289.9 2386.33   299.9 2382.18   319.9 2382.48   359.9 2393.57
   429.9 2396.55   439.9 2396.07   449.9 2393.05   478.6 2376.96   489.9 2375.62
   493.6 2376.05   569.9 2391.77   599.9 2395.53   619.9 2395.09   659.9  2387.5
   679.9 2389.27   689.9 2393.39   729.9 2417.78   779.8 2444.18   839.8 2484.11
   859.8 2494.71   889.8 2506.35   919.8 2505.25   929.8 2508.17  1009.8  2543.1
#Mann= 3 , 0 , 0
       0      .1       0   478.6    .045       0   493.6      .1       0
Bank Sta=478.6,493.6
XS Rating Curve= 0 ,0
Exp/Cntr=0.3,0.1

Type RM Length L Ch R = 1 ,1394.5  ,382.3,388.6,394.6
XS GIS Cut Line= 2
      2156486.13      399754.259     2155595.082      399801.511
#Sta/Elev= 30
       0 2523.94    50.1 2491.51   130.3 2450.33   220.6 2399.72   240.6 2389.65
   260.7 2380.68   290.8 2369.22   300.8 2367.08   310.8 2367.19   320.8 2369.92
   340.9 2378.19   350.9 2381.33   360.9 2383.31   441.1 2385.02   451.2 2384.48
   461.2 2382.45   491.3  2370.8   501.7 2367.89   511.3 2367.23   516.7 2367.85
   531.4 2370.59   551.4 2375.96   621.6 2411.08   661.7 2429.88   711.8 2451.85
     772 2476.15   862.2 2509.48   872.2  2512.4   882.3 2512.94   892.3  2511.4
#Mann= 3 , 0 , 0
       0      .1       0   501.7    .045       0   516.7      .1       0
#XS Ineff= 2 , 0
          437.56 2448.99
Permanent Ineff=
       F       F
Bank Sta=501.7,516.7
XS Rating Curve= 0 ,0
Exp/Cntr=0.3,0.1

Type RM Length L Ch R = 1 ,1006    ,441.5,424.3,407
XS GIS Cut Line= 3
     2156540.133      399517.996      2155883.66      399386.364
     2155579.894      399674.942
#Sta/Elev= 30
       0 2569.89      50 2543.75    89.9 2526.43   119.9 2515.91   159.9 2503.64
   209.9  2484.2   259.8 2471.43   279.8 2465.52   299.8 2457.65   309.8 2452.76
   329.8  2440.8   339.8 2432.68   349.8 2423.32   389.7  2384.6   419.7 2361.39
   429.7 2354.27     434 2352.93   439.7 2351.15     449 2351.97   469.7 2354.96
   589.6 2362.97   639.6 2369.34   669.5 2374.84   759.3  2398.2   859.1 2422.66
     909 2437.63  1008.7 2469.83  1018.7 2472.27  1038.6 2475.53  1088.5 2479.59
#Mann= 3 , 0 , 0
       0      .1       0     434    .045       0     449      .1       0
Bank Sta=434,449
XS Rating Curve= 0 ,0
Exp/Cntr=0.3,0.1

Type RM Length L Ch R = 1 ,581.7   ,557.4,548.9,540.1
XS GIS Cut Line= 2
     2156298.807      398859.836     2155385.821      399377.926
#Sta/Elev= 30
       0 2473.95    40.4 2466.17   100.9 2461.22   141.3 2456.77   151.4 2454.52
   161.5 2450.62   171.6 2444.76   181.7 2437.07   201.9 2417.91     212 2411.97
   242.2 2403.14   262.4 2395.77   302.8 2378.55   373.5 2345.34   419.8 2331.84
   423.9 2331.01   434.8 2331.62   464.3 2338.29   504.7 2340.22   514.8 2342.07
   555.2 2361.08   575.3 2365.16   635.9 2368.36   696.5 2363.54   726.8 2366.05
   767.1  2378.1     858 2413.01   888.2 2422.91   999.3 2453.37  1049.7 2465.46
#Mann= 3 , 0 , 0
       0      .1       0   419.8    .045       0   434.8      .1       0
Bank Sta=419.8,434.8
XS Rating Curve= 0 ,0
Exp/Cntr=0.3,0.1

Type RM Length L Ch R = 1 ,32.8    ,32.1,32.8,33.4
XS GIS Cut Line= 3
     2156291.588      398792.989     2155675.724        398565.9
     2155303.788      399035.392
#Sta/Elev= 30
       0 2459.39    49.7 2439.24    99.4  2421.3   159.1 2396.78     189    2387
   238.7 2367.54   278.5 2352.93   298.4 2346.72   308.3 2344.48   397.8 2334.77
   427.6 2332.54   477.4 2330.35   556.9 2323.34   626.6  2321.3   656.4 2322.18
   676.4 2324.56   686.4 2324.69   743.6 2318.27   756.2    2318   758.6 2318.12
   836.1 2324.35     856 2327.31     876 2332.68     906 2342.53   975.8 2357.57
  1045.7 2376.12  1145.6 2400.97  1205.4 2413.13  1225.4 2414.98  1255.4 2416.41
#Mann= 3 , 0 , 0
       0     .08       0   743.6    .045       0   758.6      .1       0
Bank Sta=743.6,758.6
XS Rating Curve= 0 ,0
Exp/Cntr=0.3,0.1

Chan Stop Cuts=-1
Use User Specified Reach Order=0
Composite Channel Slope=5